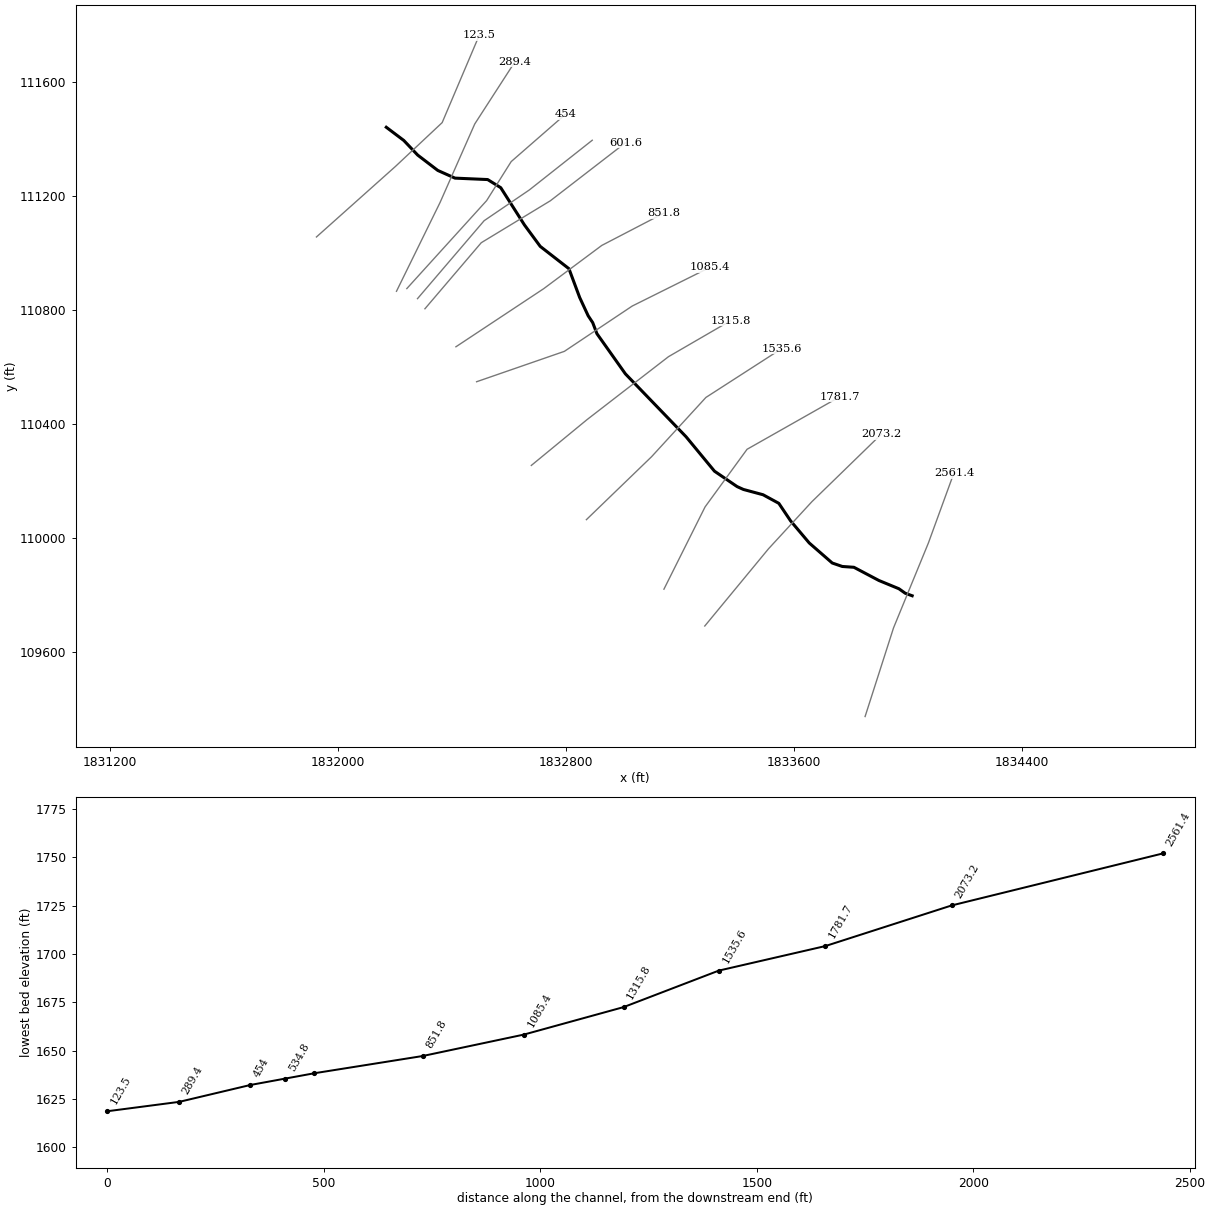
--- Jump Branch.prj (project) ---

Proj Title=Jump Branch
Current Plan=p01
Default Exp/Contr=0,0
English Units
Geom File=g01
Flow File=f01
Plan File=p01
BEGIN DESCRIPTION:
END DESCRIPTION:
DSS Export Rating Curves= 0
DSS Export Rating Curve Sorted= 0
DSS Export Volume Flow Curves= 0
DXF OffsetX= 0
DXF OffsetY= 0
DXF ScaleX= 0
DXF ScaleY= 0

--- Jump Branch.p01 (plan) ---

Plan Title=Floodplain
Program Version=4.00
Geom File=g01
Flow File=f01
K Sum by GR=0
Std Step Tol=0.01
Critical Tol=0.01
Num of Std Step Trials=20
Max Error Tol=0.3
Flow Tol Ratio=0.001
Split Flow NTrial=30
Split Flow Tol=0.02
Split Flow Ratio=0.02
Log Output Level=0
Friction Slope Method=1
Unsteady Friction Slope Method=2
Unsteady Bridges Friction Slope Method=1
Global Log Level=0
CheckData=False
Run HTab=0
Run UNet=0
Run PostProcess=0
UNET Theta=0
UNET Theta Warmup=0
UNET ZTol=0
UNET ZSATol=0
UNET MxIter=0
UNET MaxInSteps=0
UNET DtIC=0
UNET DtMin=0
UNET MaxCRTS=0
UNET WFStab=0
UNET SFStab=0
UNET WFX=0
UNET SFX=0
UNET DSS MLevel=0
UNET DZMax Abort=0
UNET Convert EG Bridges=0
UNET Use Existing IB Tables=0
UNET Froude Limit=0
UNET Froude Power=0
Write IC File=0
Echo Input=False
Echo Output=False
Write Detailed=0

--- Jump Branch.f01 (steady flow) ---

Flow Title=NFF Regression Equation
Program Version=4.00
Number of Profiles=1
Profile Names=P100yr
River Rch & RM=Jump Branch,Main      ,2561.4
555.7605
River Rch & RM=Jump Branch,Main      ,1781.7
583.7960
River Rch & RM=Jump Branch,Main      ,289.4
636.6749
Boundary for River Rch & Prof#=Jump Branch,Main      ,1
Up Type=0
Dn Type=3
Dn Slope=0.050141

--- Jump Branch.g01 (geometry) ---

Geom Title=USGS 10m DEM
Program Version=4.00

River Reach=Jump Branch     ,Main
Reach XY= 30
     1834015.887      109797.803     1833991.505      109806.696
     1833969.377      109822.465     1833899.029      109851.474
     1833811.382      109897.808      1833770.53       109900.68
     1833735.238      109912.829     1833654.484      109983.204
     1833588.963      110060.901     1833547.694      110122.347
     1833492.389      110152.497     1833423.226      110171.141
     1833401.174      110181.164     1833321.744      110235.267
     1833222.152      110355.976     1833009.049      110576.897
     1832909.014       110718.03     1832894.179      110756.922
     1832878.341      110780.778      1832848.39      110845.238
     1832810.782      110946.168     1832709.944      111024.553
     1832654.614       111099.73     1832571.313      111230.627
     1832525.354      111259.177     1832410.695      111264.204
     1832350.344       111291.17      1832279.72      111345.101
     1832230.926      111396.463     1832169.437      111442.818

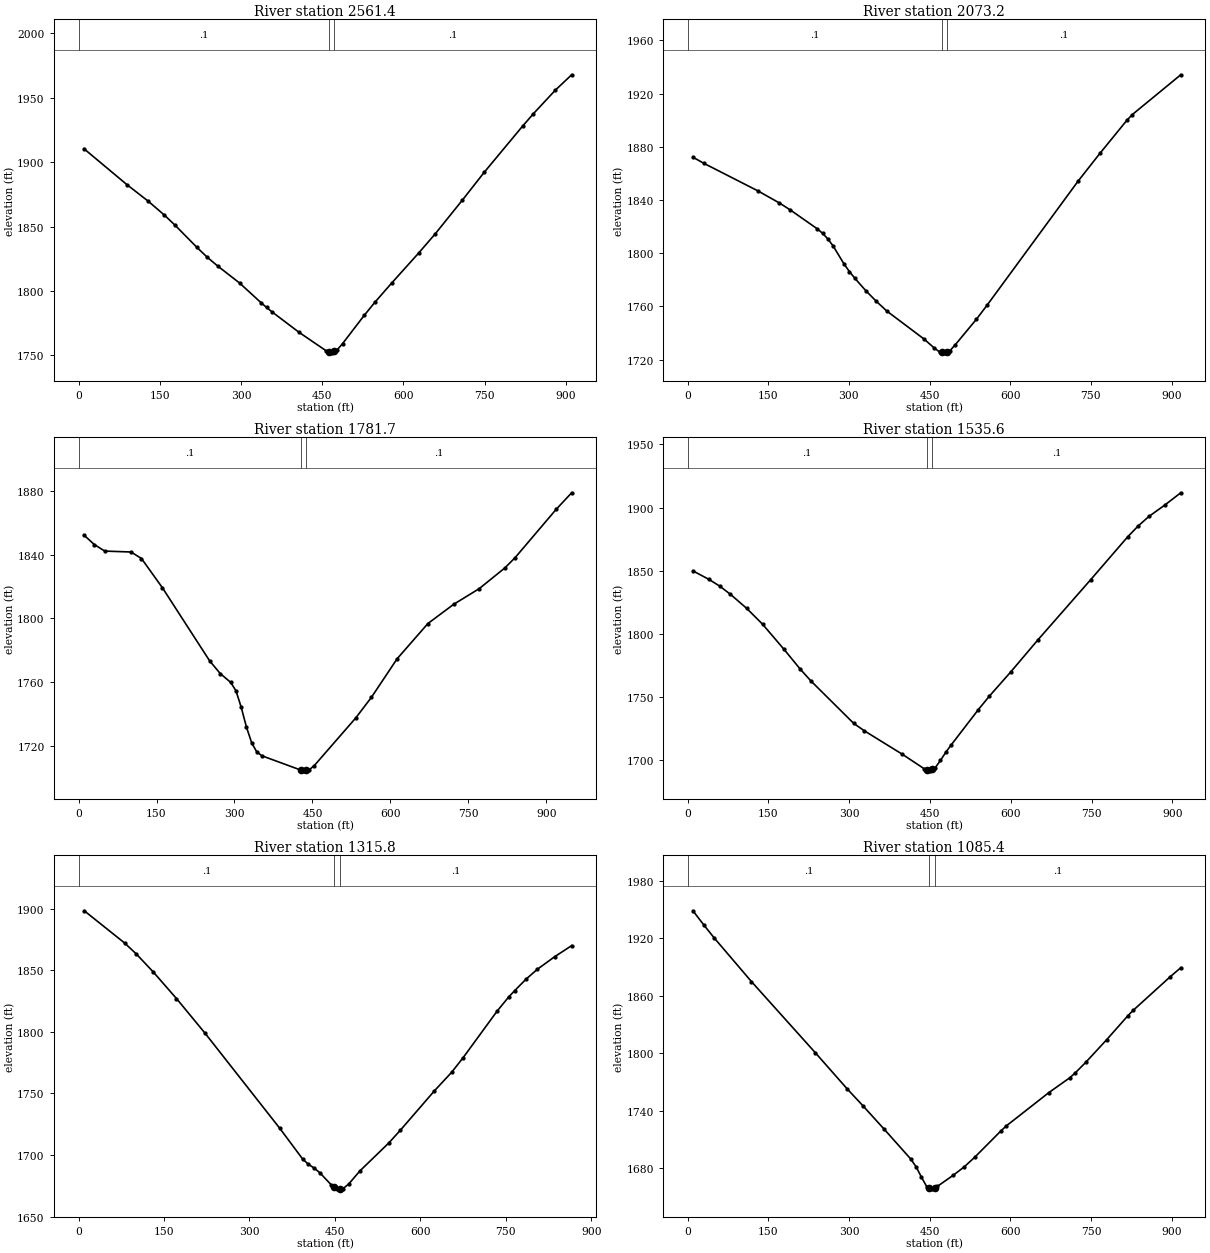
Type RM Length L Ch R = 1 ,2561.4  ,495.4,488.3,481.1
XS GIS Cut Line= 4
     1833850.592      109373.772     1833950.463      109685.131
     1834072.589       109982.46     1834162.392      110228.688
#Sta/Elev= 30
     9.9 1910.56    89.2 1882.71   128.8 1869.75   158.5 1859.01   178.4 1851.09
     218 1834.19   237.8 1826.23   257.6 1819.24   297.3 1806.28     337 1790.98
   347.1 1787.33   357.1 1783.91   407.3 1767.94   457.6 1753.53   462.6 1752.79
   467.6 1752.05   472.6 1753.22   477.7 1754.42   487.7 1759.29   527.9 1781.35
     548  1791.7   578.1 1806.17   628.3 1829.66   658.5 1844.39   708.9 1870.71
   749.2  1892.3   819.8 1928.01   839.9 1937.72   880.3 1955.96   910.5 1967.93
#Mann= 3 , 0 , 0
       0      .1       0   462.6    .045       0   472.6      .1       0
Bank Sta=462.6,472.6
XS Rating Curve= 0 ,0
Exp/Cntr=0.3,0.1

Type RM Length L Ch R = 1 ,2073.2  ,288.9,291.4,293.9
XS GIS Cut Line= 4
     1833287.699      109691.644     1833511.272      109962.515
     1833663.601      110127.963     1833908.086      110365.724
#Sta/Elev= 30
      10 1872.15    30.1 1867.61   130.5 1846.92   170.6  1837.8   190.7 1832.61
   240.8 1818.44   250.9 1815.03   260.9 1810.71   270.9 1805.27     291 1791.84
     301 1786.16   311.1 1781.11   331.2 1771.93   351.2 1763.72   370.8 1756.42
   439.2 1735.62   458.8  1728.7   468.6 1725.76   473.3 1725.44   478.3  1725.1
   483.3 1725.98   488.1 1726.83   497.9 1731.22     537 1750.32   556.6 1760.74
   726.6 1854.43   766.7 1875.03   816.8 1899.89   826.9  1904.2   917.1 1934.16
#Mann= 3 , 0 , 0
       0      .1       0   473.3    .045       0   483.3      .1       0
Bank Sta=473.3,483.3
XS Rating Curve= 0 ,0
Exp/Cntr=0.3,0.1

Type RM Length L Ch R = 1 ,1781.7  ,248.4,246.2,243.9
XS GIS Cut Line= 4
     1833144.315      109820.934     1833288.786      110109.876
     1833436.147      110312.135     1833762.651      110497.058
#Sta/Elev= 30
    10.1 1852.32    30.3 1846.31    50.5 1842.17     101  1841.6   121.1 1837.51
   161.5 1819.06   252.4 1773.11   272.6 1765.22   292.8 1759.64   302.9 1754.34
     313 1743.97     323 1731.59   333.1 1721.65   343.1 1715.83   353.1  1713.5
   428.2 1704.49   433.2 1704.09   438.2 1704.36   443.2 1704.63   453.2 1707.29
   533.3 1737.36   563.3 1750.25   612.8 1774.51     672 1796.65   721.4 1808.69
   770.8 1818.59   820.2 1831.64   839.9 1838.11   918.9 1868.48   948.5 1878.81
#Mann= 3 , 0 , 0
       0      .1       0   428.2    .045       0   438.2      .1       0
Bank Sta=428.2,438.2
XS Rating Curve= 0 ,0
Exp/Cntr=0.3,0.1

Type RM Length L Ch R = 1 ,1535.6  ,223.2,219.8,216.4
XS GIS Cut Line= 4
     1832872.084      110065.081     1833100.974       110286.13
     1833291.676      110494.168      1833556.49      110664.821
#Sta/Elev= 30
     9.9 1849.84    39.8 1843.04    59.7 1837.74    79.6 1831.22   109.4 1820.24
   139.2 1807.55     179 1787.65   208.8 1772.13   228.7  1762.7   308.3 1729.01
   328.3 1723.05   398.8 1704.47   439.2 1693.03   444.2  1692.2   449.2 1691.38
   454.2  1692.5   459.3 1693.65   469.4  1699.6   479.5 1706.22   489.5 1712.01
   539.9 1739.98   560.1 1750.53   600.4 1770.01   649.6 1794.81   748.1 1842.76
     817 1876.83   836.7 1885.52   856.4 1892.96   885.9 1901.99   915.5 1911.72
#Mann= 3 , 0 , 0
       0      .1       0   444.2    .045       0   454.2      .1       0
Bank Sta=444.2,454.2
XS Rating Curve= 0 ,0
Exp/Cntr=0.3,0.1

Type RM Length L Ch R = 1 ,1315.8  ,231.7,230.4,229.1
XS GIS Cut Line= 4
     1832678.701       110255.46     1832873.977       110416.02
     1833160.382      110637.333     1833377.355      110763.178
#Sta/Elev= 30
    10.1 1898.46    80.9 1872.28   101.1 1863.53   131.5 1848.59   171.9 1827.17
   222.5 1798.74   353.4 1721.59   393.6 1696.59   403.6 1692.44   413.7 1689.33
   423.7 1685.52   443.8 1675.63   448.9 1674.04   453.9 1672.49   458.9 1672.52
   463.9 1672.55     474 1676.29   494.1 1687.14   544.4 1709.66   564.5 1719.91
   624.8 1752.19   654.9 1767.18     675 1779.04   735.2 1817.19   755.2 1828.48
   765.3 1833.42   785.3  1842.8   805.4 1850.93   835.5 1861.05   865.6 1870.14
#Mann= 3 , 0 , 0
       0      .1       0   448.9    .045       0   458.9      .1       0
Bank Sta=448.9,458.9
XS Rating Curve= 0 ,0
Exp/Cntr=0.3,0.1

Type RM Length L Ch R = 1 ,1085.4  ,232.5,233.6,234.7
XS GIS Cut Line= 4
     1832486.553      110549.303     1832794.696      110655.976
     1833032.976      110815.075     1833305.418      110950.703
#Sta/Elev= 30
     9.9 1948.48    29.6 1934.08    49.4 1920.16   118.6 1874.65   237.2 1800.49
   296.4 1762.77   326.1 1744.88   365.6 1720.44     415 1689.31   424.9 1681.19
   434.8 1670.46   444.6 1660.48   449.5 1659.38   454.5 1658.26   459.5 1659.57
   464.4 1660.84     494 1672.49   513.8 1680.96   533.6  1691.1     583 1718.99
   592.8 1724.05   671.5 1758.65   710.8 1774.28   720.6 1779.21   740.2 1790.26
   779.5 1814.13   818.8 1839.09   828.6 1844.63   897.3 1879.63   916.9 1889.04
#Mann= 3 , 0 , 0
       0      .1       0   449.5    .045       0   459.5      .1       0
Bank Sta=449.5,459.5
XS Rating Curve= 0 ,0
Exp/Cntr=0.3,0.1

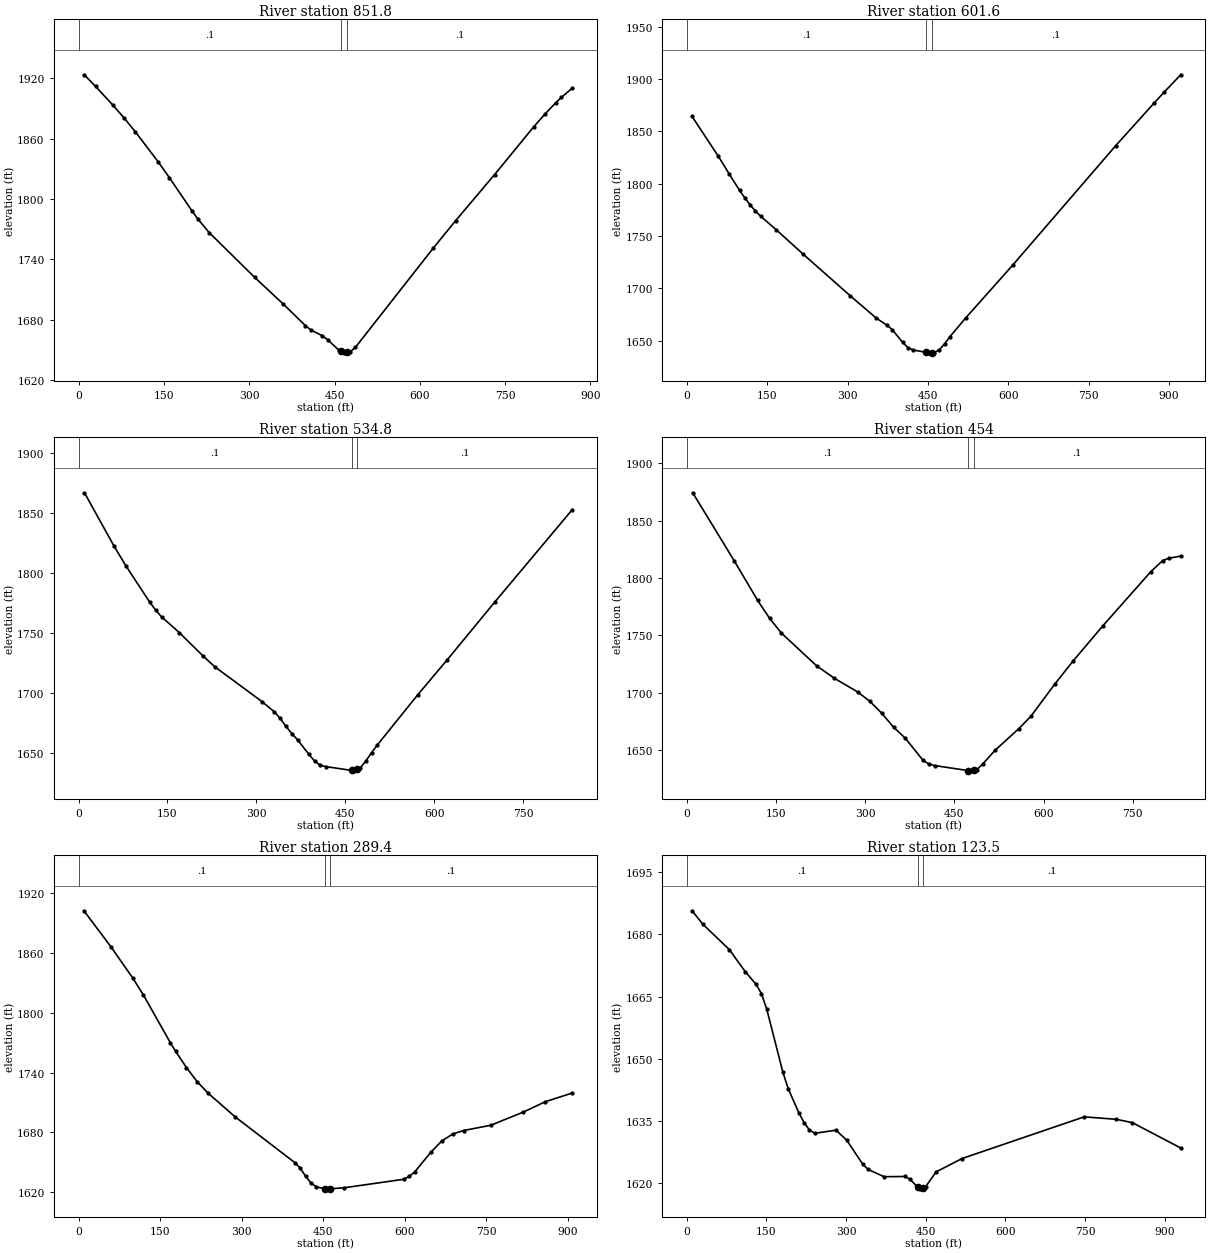
Type RM Length L Ch R = 1 ,851.8   ,252.2,250.3,248.3
XS GIS Cut Line= 4
     1832413.993      110672.049     1832722.095      110876.004
      1832926.05      111027.886     1833143.024      111140.712
#Sta/Elev= 30
      10 1923.29      30 1911.67    59.9 1893.48    79.9 1880.51    99.9 1866.64
   139.8 1837.03   159.8 1821.07   199.7 1787.93   209.7 1780.14   229.7 1766.59
   309.6 1722.12   359.5 1695.82   398.8 1674.23   408.6 1669.84   428.2 1664.23
     438 1660.19   457.5  1649.9   462.3 1648.56   467.3 1647.17   472.3 1647.53
   477.1 1647.88   486.9 1652.74   623.8 1751.28   662.9 1778.36   731.4 1824.16
   799.9 1871.36   819.4 1883.96     839 1895.49   848.8 1900.78   868.3 1910.16
#Mann= 3 , 0 , 0
       0      .1       0   462.3    .045       0   472.3      .1       0
Bank Sta=462.3,472.3
XS Rating Curve= 0 ,0
Exp/Cntr=0.3,0.1

Type RM Length L Ch R = 1 ,601.6   ,65.7,66.8,67.8
XS GIS Cut Line= 4
     1832305.118      110805.506     1832502.864      111037.379
     1832745.576      111184.739     1833009.194      111388.254
#Sta/Elev= 30
     9.8 1864.07      59 1825.87    78.6 1809.45    98.3 1793.55   108.1 1786.37
     118 1779.73   127.8 1773.77   137.6 1768.86   167.1  1755.7   216.3 1732.87
   304.7 1692.87   353.7 1671.35   373.3 1664.72   383.1 1660.54   402.7  1648.3
   412.4 1643.32   422.2 1640.97   446.6 1638.74   451.6 1638.25   456.6 1638.32
   461.4 1638.39   471.2 1641.14     481 1646.85   490.8 1653.59   520.1 1671.39
   608.9  1722.5   800.6  1836.3   871.3 1876.47   891.4 1887.69   921.7  1903.9
#Mann= 3 , 0 , 0
       0      .1       0   446.6    .045       0   456.6      .1       0
Bank Sta=446.6,456.6
XS Rating Curve= 0 ,0
Exp/Cntr=0.3,0.1

Type RM Length L Ch R = 1 ,534.8   ,72.5,80.8,89.1
XS GIS Cut Line= 4
     1832279.082      110841.063     1832513.024      111114.731
     1832671.928      111222.874     1832892.628      111397.228
#Sta/Elev= 30
      10 1866.64      60 1822.22      80 1805.84     120 1775.79     130 1769.18
     140 1763.56     170 1750.44     210 1731.02     230 1721.99     310 1692.91
     330 1684.75     340 1679.26     350 1672.52     360 1666.38   369.6 1661.32
   388.9  1649.1   398.5 1643.58   408.1 1640.07   417.7    1639   460.7 1635.86
   465.7  1635.5   470.7 1636.75   475.4 1637.93     485 1643.75   494.6 1650.73
   504.2 1656.99   572.3 1698.61   622.6 1728.04   702.9 1776.09   833.5 1852.74
#Mann= 3 , 0 , 0
       0      .1       0   460.7    .045       0   470.7      .1       0
Bank Sta=460.7,470.7
XS Rating Curve= 0 ,0
Exp/Cntr=0.3,0.1

Type RM Length L Ch R = 1 ,454     ,161.6,164.6,167.6
XS GIS Cut Line= 4
     1832241.563      110876.375     1832521.852      111185.355
     1832607.925      111322.189     1832797.727      111487.715
#Sta/Elev= 30
     9.9 1874.23    79.5 1815.18   119.2 1780.46   139.1    1765   158.9 1752.18
   218.5 1723.49   248.3 1712.74     288 1700.61   307.9 1692.65   327.8 1682.35
   347.6 1670.24   367.5 1660.55   397.3 1641.32   407.2 1638.09   417.2 1636.74
   472.8 1632.42   477.8 1632.18   482.8 1632.75   487.9 1633.32     498  1638.3
   518.2 1649.94   558.6 1669.02   578.8 1679.74   619.1 1707.83   649.3 1727.56
   699.7  1758.4   780.3  1805.5   800.4 1815.25   810.5 1817.19   830.7 1819.12
#Mann= 3 , 0 , 0
       0      .1       0   472.8    .045       0   482.8      .1       0
Bank Sta=472.8,482.8
XS Rating Curve= 0 ,0
Exp/Cntr=0.3,0.1

Type RM Length L Ch R = 1 ,289.4   ,174,165.9,157.9
XS GIS Cut Line= 4
     1832205.254      110866.903     1832358.394      111178.961
     1832480.025      111454.333     1832621.331      111673.051
#Sta/Elev= 30
     9.9 1902.61    59.6 1866.46    99.3 1835.48   119.2 1818.26   168.8 1770.31
   178.8 1761.39   198.6 1745.18   218.5  1730.9   238.4 1719.49     288 1695.81
   397.8 1649.87   407.8 1644.31   417.9 1636.14   427.9 1629.17   437.9 1625.39
     453  1623.6     458 1623.43     463 1623.52   488.1 1624.45   598.5 1633.04
   608.5 1635.85   618.5 1640.32   648.6 1660.26   668.7  1671.6   688.7 1678.48
   708.7 1681.99   758.8 1687.26   818.9 1700.57     859 1710.88     909 1719.72
#Mann= 3 , 0 , 0
       0      .1       0     453    .045       0     463      .1       0
Bank Sta=453,463
XS Rating Curve= 0 ,0
Exp/Cntr=0.3,0.1

Type RM Length L Ch R = 1 ,123.5   ,120,123.5,126.9
XS GIS Cut Line= 4
     1831924.237      111057.593     1832201.328      111304.999
     1832365.638      111459.111     1832496.042      111766.142
#Sta/Elev= 30
      10 1685.72    30.1 1682.48    80.3 1676.31   110.4 1670.96   130.5 1667.96
   140.6  1665.7   150.6 1661.93   180.7 1646.83   190.8  1642.8   210.8 1636.99
   220.9 1634.55   230.9  1632.8     241 1631.99   281.1 1632.74   301.2 1630.32
   331.3 1624.54   341.3 1623.27   371.5 1621.51   410.6 1621.56   420.4 1620.89
     435 1618.98     440 1618.58     445 1618.84   449.8 1619.09   469.4 1622.66
   518.4  1625.9   748.4 1635.96     809 1635.37   839.3 1634.56   930.3 1628.44
#Mann= 3 , 0 , 0
       0      .1       0     435    .045       0     445      .1       0
Bank Sta=435,445
XS Rating Curve= 0 ,0
Exp/Cntr=0.3,0.1

Chan Stop Cuts=-1
Use User Specified Reach Order=0